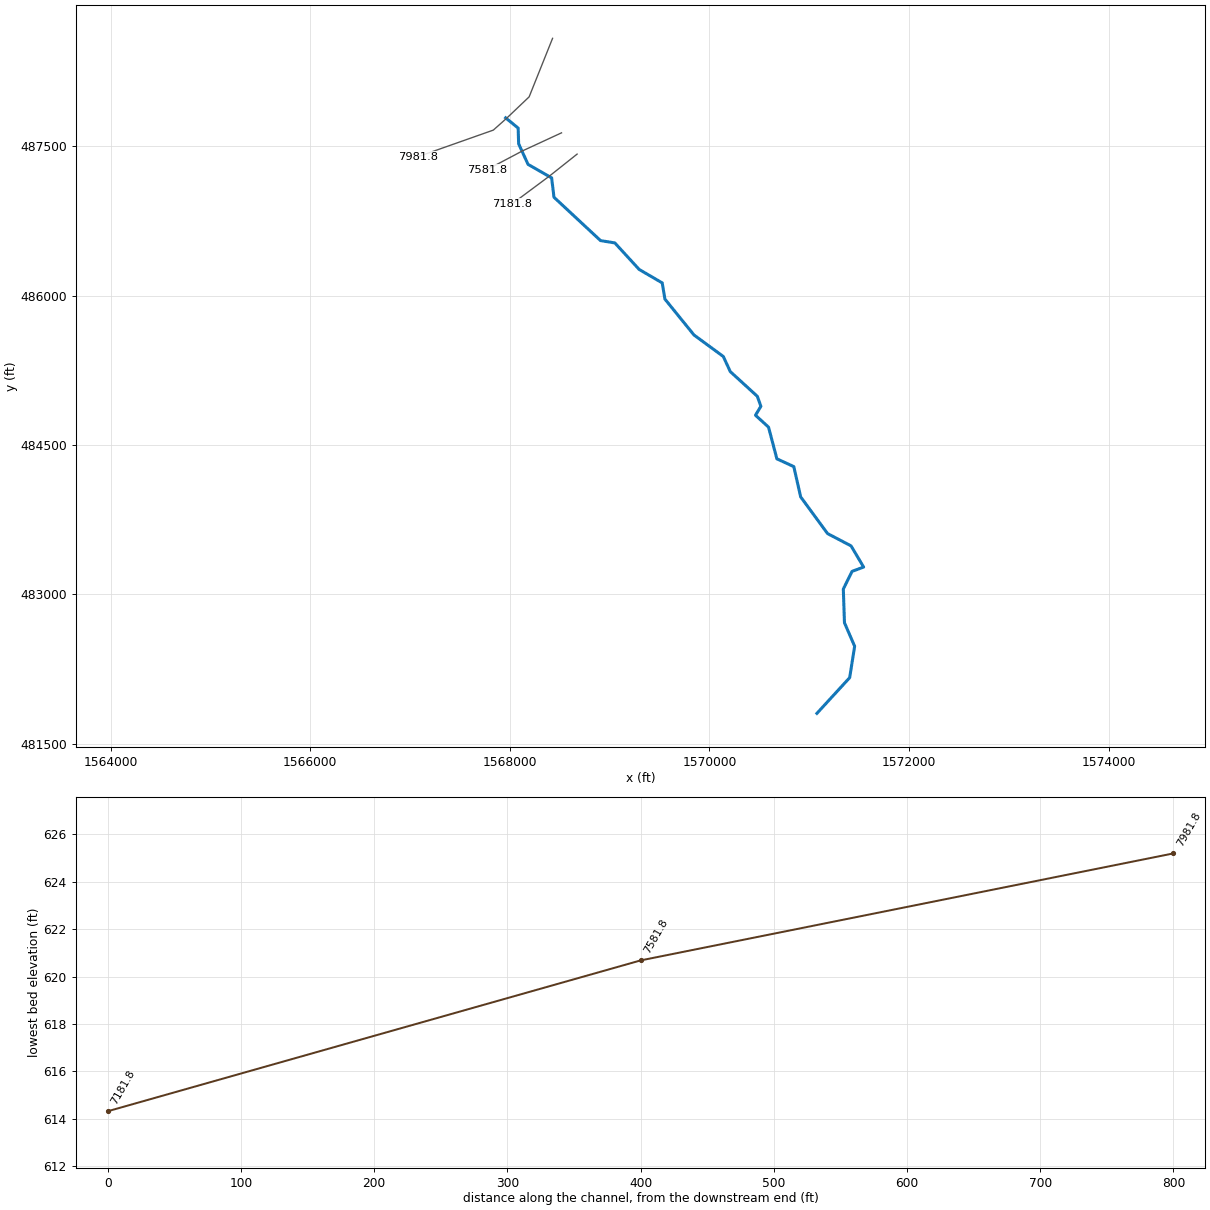
--- PRICECR.prj (project) ---

Proj Title=PRICECR
Current Plan=p01
Default Exp/Contr=0,0
English Units
Geom File=g01
Flow File=f01
Plan File=p01
BEGIN DESCRIPTION:
END DESCRIPTION:
DSS Export Rating Curves= 0
DSS Export Rating Curve Sorted= 0
DSS Export Volume Flow Curves= 0
DXF OffsetX= 0
DXF OffsetY= 0
DXF ScaleX= 0
DXF ScaleY= 0

--- PRICECR.p01 (plan) ---

Plan Title=Floodplain
Program Version=4.00
Geom File=g01
Flow File=f01
K Sum by GR=0
Std Step Tol=0.01
Critical Tol=0.01
Num of Std Step Trials=20
Max Error Tol=0.3
Flow Tol Ratio=0.001
Split Flow NTrial=30
Split Flow Tol=0.02
Split Flow Ratio=0.02
Log Output Level=0
Friction Slope Method=1
Unsteady Friction Slope Method=2
Unsteady Bridges Friction Slope Method=1
Global Log Level=0
CheckData=False
Run HTab=0
Run UNet=0
Run PostProcess=0
UNET Theta=0
UNET Theta Warmup=0
UNET ZTol=0
UNET ZSATol=0
UNET MxIter=0
UNET MaxInSteps=0
UNET DtIC=0
UNET DtMin=0
UNET MaxCRTS=0
UNET WFStab=0
UNET SFStab=0
UNET WFX=0
UNET SFX=0
UNET DSS MLevel=0
UNET DZMax Abort=0
UNET Convert EG Bridges=0
UNET Use Existing IB Tables=0
UNET Froude Limit=0
UNET Froude Power=0
Write IC File=0
Echo Input=False
Echo Output=False
Write Detailed=0

--- PRICECR.f01 (steady flow) ---

Flow Title=NFF Regression Equation
Program Version=4.00
Number of Profiles=1
Profile Names=P100yr
River Rch & RM=PRICECR,Main      ,7981.8
     366
River Rch & RM=PRICECR,Main      ,7181.8
     392
Boundary for River Rch & Prof#=PRICECR,Main      ,1
Up Type=0
Dn Type=3
Dn Slope=0.013602

--- PRICECR.g01 (geometry) ---

Geom Title=USGS 10m DEM
Program Version=4.00

River Reach=PRICECR     ,Main
Reach XY= 30
     1567957.656      487784.605     1568083.261      487681.852
     1568087.964      487524.752     1568182.136      487317.707
     1568418.816      487181.658     1568442.198      486987.279
     1568908.930      486551.787     1569052.093      486528.633
     1569296.155      486262.072     1569526.871      486127.232
     1569554.145      485964.226     1569845.273      485603.962
     1570139.573      485387.677     1570208.709      485236.721
     1570479.956      484988.153     1570515.694      484887.874
     1570461.781      484797.808     1570592.482      484678.395
     1570676.163      484360.164     1570845.513      484282.149
     1570914.648      483977.701     1571183.862      483609.616
     1571419.500      483485.925     1571545.539      483272.990
     1571429.677      483229.933     1571341.998      483052.227
     1571353.428      482713.919     1571455.589      482477.812
     1571405.643      482162.245     1571077.297      481803.715

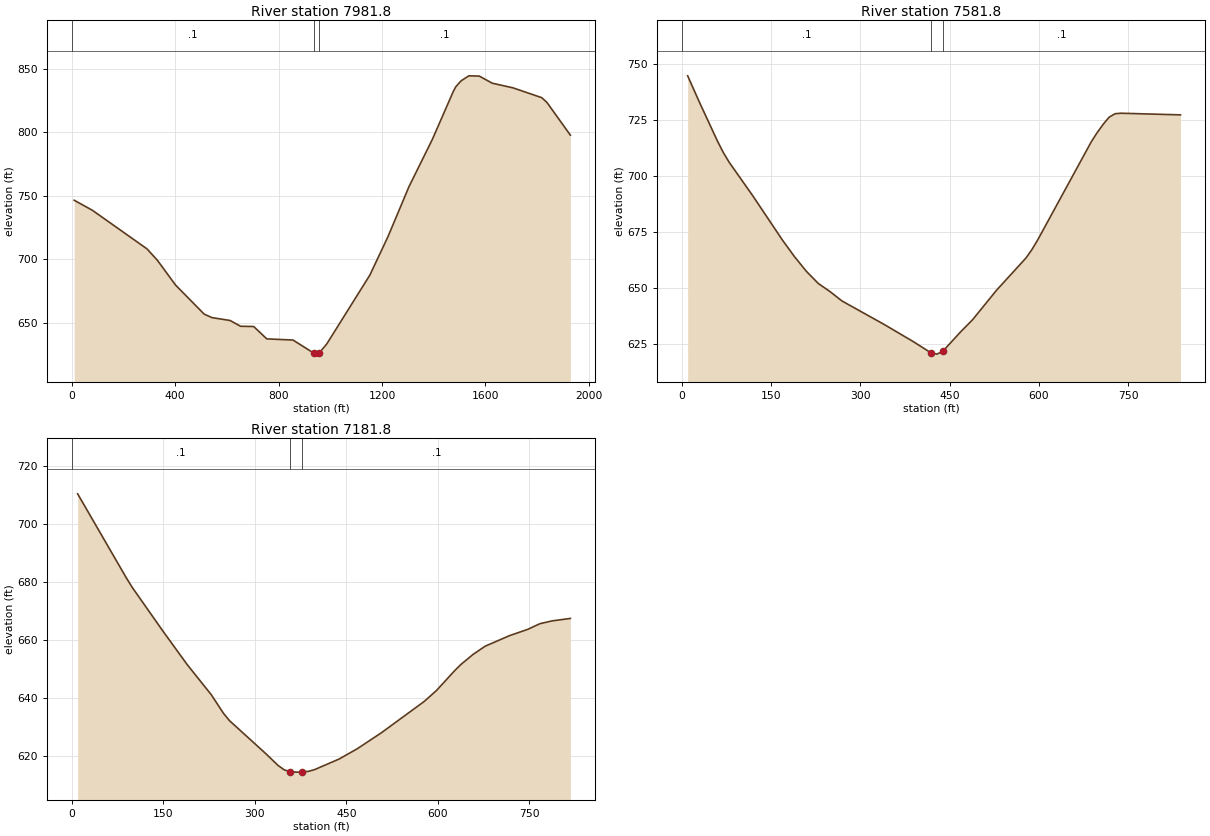
Type RM Length L Ch R = 1 ,7981.8,408.5,400,393.7
XS GIS Cut Line= 5
     1568428.102      488583.255     1568193.184      487995.421
     1567965.623      487778.561     1567834.518      487661.647
     1567075.241      487393.109
#Sta/Elev= 30
    10.0  746.34    80.4  738.42   291.4  708.07   331.6  699.09   401.9  679.57
   512.5  656.70   542.6  653.95   612.9  651.67   653.3  647.13   704.0  646.94
   754.7  637.21   856.1  636.28   937.4  625.86   947.4  625.20   957.4  626.11
   986.4  633.17  1153.2  687.41  1223.7  717.90  1304.3  756.97  1394.9  794.29
  1475.4  831.79  1485.5  835.67  1505.6  840.28  1535.8  844.27  1576.1  844.07
  1626.4  838.46  1706.9  834.79  1817.7  827.08  1837.8  823.34  1928.4  797.57
#Mann= 3 , 0 , 0
       0     0.1       0   937.4   0.045       0   957.4     0.1       0
Bank Sta=   937.4,   957.4
Exp/Cntr=0.3,0.1

Type RM Length L Ch R = 1 ,7581.8,395.7,400,392.8
XS GIS Cut Line= 3
     1568517.831      487634.186     1568128.741      487453.911
     1567767.102      487262.497
#Sta/Elev= 30
    10.0  744.93    29.9  733.08    59.8  715.95    69.8  710.72    79.8  706.32
   119.7  691.26   169.5  671.50   189.5  664.20   209.4  657.67   229.4  652.25
   249.3  648.58   269.3  644.41   339.1  634.09   388.9  626.30   418.8  621.25
   428.8  620.68   438.8  621.99   468.7  630.65   488.7  636.03   528.6  649.09
   578.5  663.63   588.5  667.39   598.5  671.84   688.3  715.56   698.3  719.68
   708.3  723.34   718.2  726.48   728.2  728.02   738.2  728.23   838.0  727.50
#Mann= 3 , 0 , 0
       0     0.1       0   418.8   0.045       0   438.8     0.1       0
Bank Sta=   418.8,   438.8
Exp/Cntr=0.3,0.1

Type RM Length L Ch R = 1 ,7181.8,7214.4,7181.8,7153.6
XS GIS Cut Line= 3
     1568674.035      487420.538     1568393.726      487197.571
     1568025.757      486923.423
#Sta/Elev= 30
     9.9  710.52    89.5  681.52    99.5  678.12   149.2  663.18   189.0  651.58
   228.8  641.07   248.7  634.66   258.7  632.09   318.4  620.64   338.3  616.61
   348.2  615.11   358.1  614.43   368.1  614.31   378.1  614.35   388.1  614.59
   398.1  615.18   438.0  618.82   467.9  622.39   507.8  627.97   577.6  638.75
   597.6  642.51   627.5  649.39   637.5  651.49   657.4  654.97   677.4  657.84
   717.3  661.49   747.2  663.67   767.2  665.63   787.1  666.59   817.0  667.45
#Mann= 3 , 0 , 0
       0     0.1       0   358.1   0.045       0   378.1     0.1       0
Bank Sta=   358.1,   378.1
Exp/Cntr=0.3,0.1